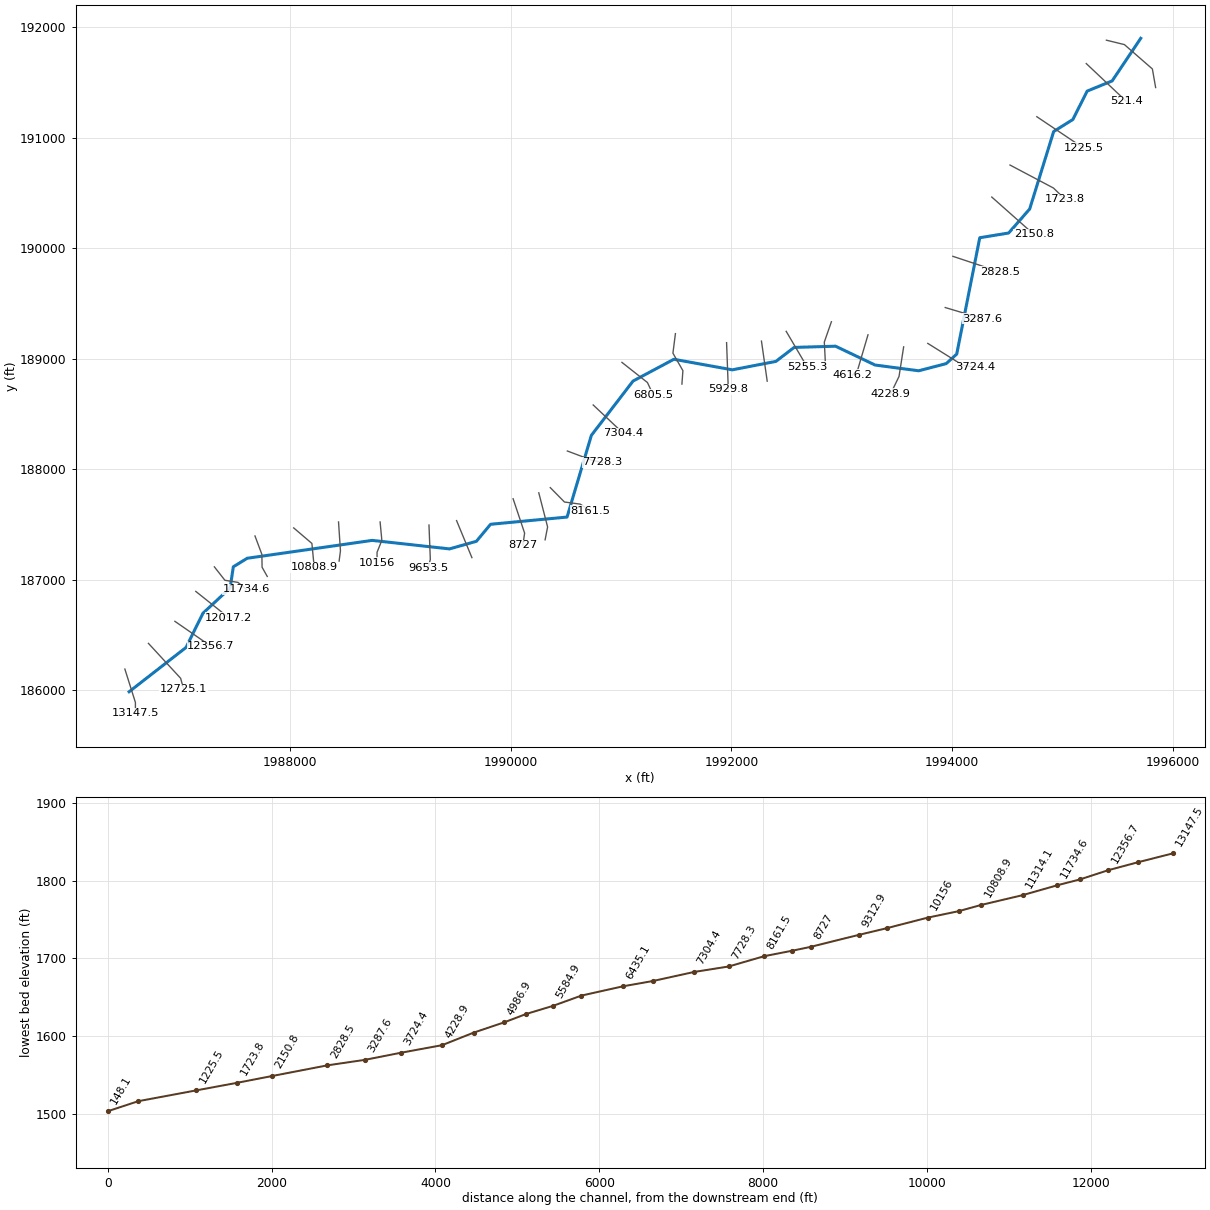
--- TOMSRN.prj (project) ---

Proj Title=TOMSRN
Current Plan=p01
Default Exp/Contr=0,0
English Units
Geom File=g01
Flow File=f01
Plan File=p01
BEGIN DESCRIPTION:
END DESCRIPTION:
DSS Export Rating Curves= 0
DSS Export Rating Curve Sorted= 0
DSS Export Volume Flow Curves= 0
DXF OffsetX= 0
DXF OffsetY= 0
DXF ScaleX= 0
DXF ScaleY= 0

--- TOMSRN.p01 (plan) ---

Plan Title=Floodplain
Program Version=4.00
Geom File=g01
Flow File=f01
K Sum by GR=0
Std Step Tol=0.01
Critical Tol=0.01
Num of Std Step Trials=20
Max Error Tol=0.3
Flow Tol Ratio=0.001
Split Flow NTrial=30
Split Flow Tol=0.02
Split Flow Ratio=0.02
Log Output Level=0
Friction Slope Method=1
Unsteady Friction Slope Method=2
Unsteady Bridges Friction Slope Method=1
Global Log Level=0
CheckData=False
Run HTab=0
Run UNet=0
Run PostProcess=0
UNET Theta=0
UNET Theta Warmup=0
UNET ZTol=0
UNET ZSATol=0
UNET MxIter=0
UNET MaxInSteps=0
UNET DtIC=0
UNET DtMin=0
UNET MaxCRTS=0
UNET WFStab=0
UNET SFStab=0
UNET WFX=0
UNET SFX=0
UNET DSS MLevel=0
UNET DZMax Abort=0
UNET Convert EG Bridges=0
UNET Use Existing IB Tables=0
UNET Froude Limit=0
UNET Froude Power=0
Write IC File=0
Echo Input=False
Echo Output=False
Write Detailed=0

--- TOMSRN.f01 (steady flow) ---

Flow Title=NFF Regression Equation
Program Version=4.00
Number of Profiles=1
Profile Names=P100yr
River Rch & RM=TOMSRN,Main      ,13147.5
517.0566
River Rch & RM=TOMSRN,Main      ,10534.9
558.4235
River Rch & RM=TOMSRN,Main      ,10156
637.9177
River Rch & RM=TOMSRN,Main      ,8161.5
680.9972
River Rch & RM=TOMSRN,Main      ,7728.3
889.8982
River Rch & RM=TOMSRN,Main      ,6805.5
904.5083
River Rch & RM=TOMSRN,Main      ,6435.1
1011.863
River Rch & RM=TOMSRN,Main      ,5929.8
1016.753
River Rch & RM=TOMSRN,Main      ,3724.4
1267.770
River Rch & RM=TOMSRN,Main      ,3724.4
1126.341
River Rch & RM=TOMSRN,Main      ,148.1
1311.931
Boundary for River Rch & Prof#=TOMSRN,Main      ,1
Up Type=0
Dn Type=3
Dn Slope=0.024759

--- TOMSRN.g01 (geometry) ---

Geom Title=USGS 10m DEM
Program Version=4.10

River Reach=TOMSRN          ,Main
Reach XY= 30
     1986543.288      185986.133     1987058.917      186386.875
     1987212.389      186697.118     1987458.223      186924.896
     1987487.352      187117.045     1987613.084      187194.341
     1988745.028      187356.146     1989445.723      187279.063
     1989689.473      187347.813     1989817.945      187501.979
     1990511.001      187567.257      1990731.14       188306.84
     1991108.917      188798.507     1991478.709      188995.556
     1992008.223      188900.069     1992403.188      188976.458
      1992568.23      189102.946     1992943.283      189113.873
     1993301.626      188943.472     1993696.591      188891.389
     1993945.758      188956.221     1994041.209      189042.431
     1994250.028      190095.671     1994511.921      190138.629
     1994702.198       190355.99     1994919.389       191057.13
     1995093.865      191166.406     1995222.813      191423.059
     1995449.351      191515.278     1995708.177        191900.7

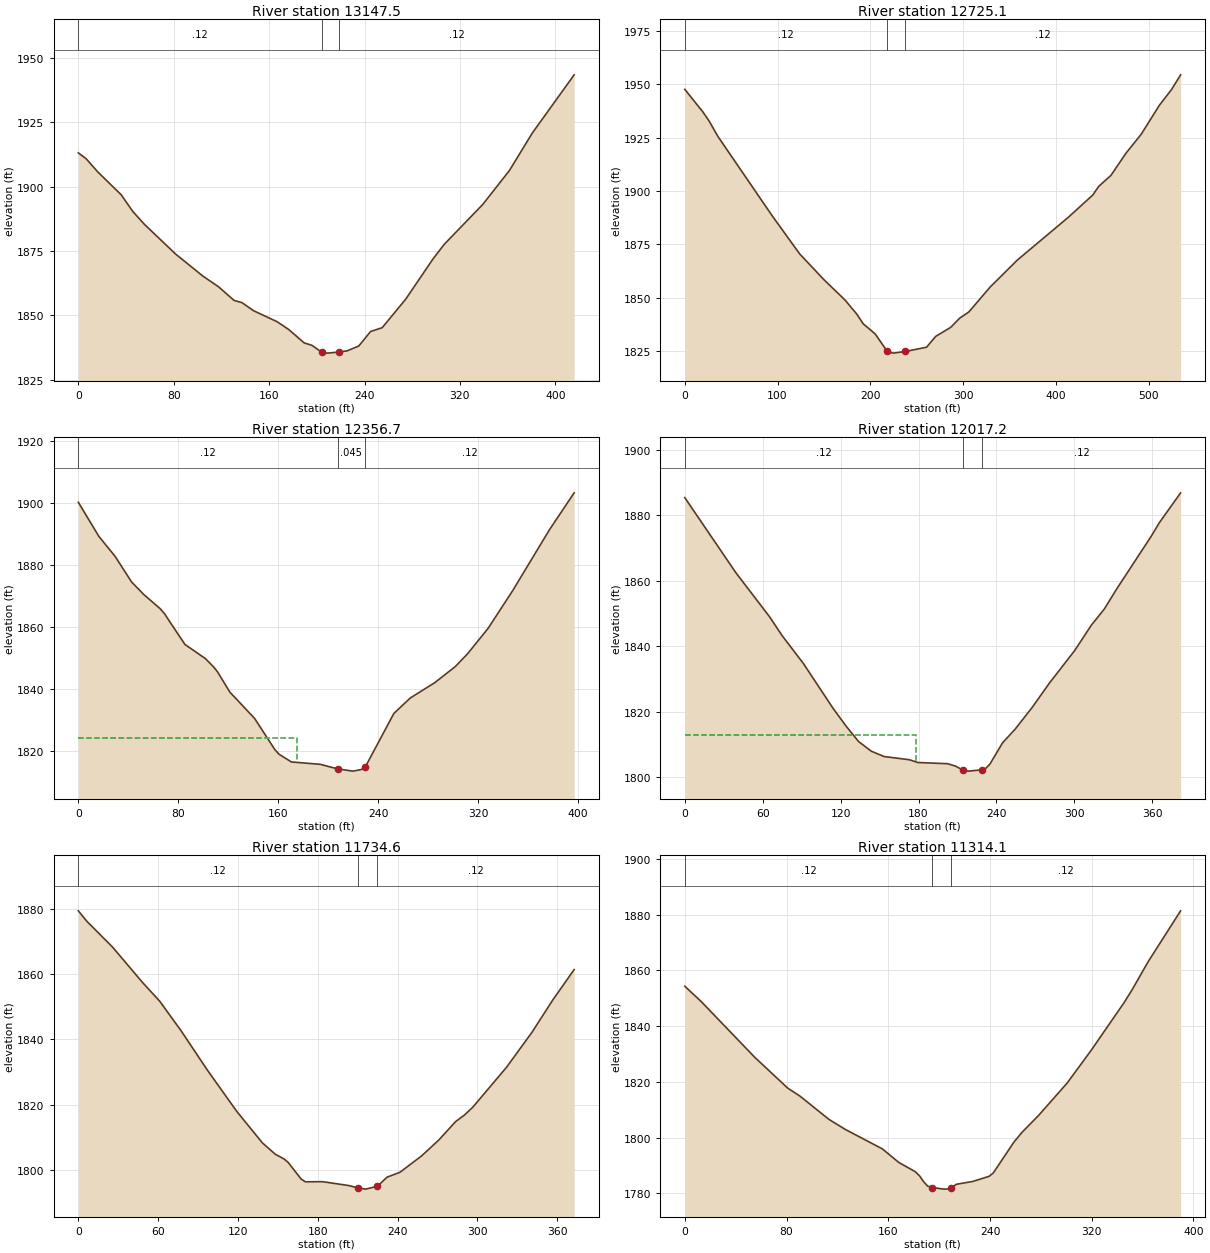
Type RM Length L Ch R = 1 ,13147.5 ,411.2,422.4,431.6
XS GIS Cut Line= 3
     1986504.784      186191.303      1986600.27       185889.22
      1986600.27      185790.262
#Sta/Elev= 30
       0 1913.13     6.5 1910.88    16.3 1905.73    35.9 1896.86    45.7 1890.34
    55.5  1885.3    81.6 1873.78   104.5  1865.2   117.6 1861.05   130.6 1855.76
   137.2 1854.89     147 1851.74   166.6  1847.5   176.4 1844.46   189.4 1839.24
     196 1838.27     204 1835.65     209 1835.26     219 1835.71   225.4 1836.14
   235.2 1838.03     245 1843.64   254.8 1845.15   274.4 1856.15   297.2 1871.73
     307 1877.64   339.2  1893.1   361.5 1906.25   380.7 1920.83   415.8 1943.47
#Mann= 3 ,-1 , 0
       0     .12       0     204    .045       0     219     .12       0
Bank Sta=204,219
XS Rating Curve= 0 ,0
Exp/Cntr=0.3,0.1

Type RM Length L Ch R = 1 ,12725.1 ,363.3,368.4,373
XS GIS Cut Line= 3
     1986718.326      186423.942     1987009.992       186107.97
      1987037.77      186007.276
#Sta/Elev= 30
       0 1947.61    19.6 1936.96    26.1 1932.83    35.8 1925.45    94.5 1888.14
   123.8 1870.49   149.8 1858.46   172.7 1848.85   185.7 1842.09   192.2 1837.74
   205.2 1832.97   218.3 1824.75   224.8 1823.95   237.8 1824.73   260.6 1826.72
   270.4 1831.77   286.7 1836.06   296.4 1840.36   306.2 1843.24     329 1854.85
   358.3  1867.5   413.7 1887.72   439.8 1898.06   446.3 1902.16   459.4 1907.28
   475.7 1917.72     492 1926.54   511.6 1940.13   524.7 1947.51   534.5  1954.4
#Mann= 3 ,-1 , 0
       0     .12       0   218.3    .045       0   237.8     .12       0
Bank Sta=218.3,237.8
XS Rating Curve= 0 ,0
Exp/Cntr=0.3,0.1

Type RM Length L Ch R = 1 ,12356.7 ,340.1,339.5,336
XS GIS Cut Line= 2
     1986957.909      186623.595     1987284.298      186397.901
#Sta/Elev= 30
       0 1900.23    16.4 1889.25    29.5 1882.75    42.6 1874.54    52.5 1870.44
    65.6 1865.88    68.9 1864.32    85.3 1854.39   101.7 1849.82   108.2 1847.17
   111.5 1845.49   121.3    1839     141 1830.57   157.4  1820.4   160.7 1818.97
   170.5  1816.5   193.5 1815.74   207.5 1814.27   219.7 1813.54   226.3 1814.04
   229.6 1814.84   252.5 1832.13   265.6  1837.1   285.3 1842.08   301.7 1847.26
   311.6 1851.42     328 1859.61   347.6 1871.73   377.1  1891.4   396.8 1903.27
#Mann= 3 ,-1 , 0
       0     .12       0   207.5    .045       0   229.6     .12       0
#XS Ineff= 2 , 0
             175 1824.31
Permanent Ineff=
       F       F
Bank Sta=207.5,229.6
XS Rating Curve= 0 ,0
Exp/Cntr=0.3,0.1

Type RM Length L Ch R = 1 ,12017.2 ,270.3,282.6,294.1
XS GIS Cut Line= 2
     1987147.145      186894.428     1987445.756      186656.581
#Sta/Elev= 30
       0  1885.4    39.2 1862.54    65.3    1849      75 1843.22    91.4 1834.69
   114.2 1821.03     124 1815.72   133.8 1810.91   143.6 1807.95   153.4 1806.32
   172.9 1805.34   179.5 1804.49   202.3 1804.13   208.8 1803.35     214 1802.18
   218.6 1801.86     229 1802.27   231.7 1802.68   234.9 1803.98   244.7 1810.51
   254.5 1814.74   267.6 1821.38   280.6 1828.66   300.2 1838.68   313.2 1846.52
     323 1851.35   332.8 1857.65   358.9 1873.45   365.4 1877.74   381.8 1886.87
#Mann= 3 ,-1 , 0
       0     .12       0     214    .045       0     229     .12       0
#XS Ineff= 2 , 0
          177.84 1812.87
Permanent Ineff=
       F       F
Bank Sta=214,229
XS Rating Curve= 0 ,0
Exp/Cntr=0.3,0.1

Type RM Length L Ch R = 1 ,11734.6 ,450.8,420.5,387.4
XS GIS Cut Line= 4
     1987315.548      187116.651     1987411.034      186995.123
     1987529.089      186976.026     1987605.478      186913.526
#Sta/Elev= 30
       0 1879.35     6.4 1876.15    25.8 1868.22    48.3  1857.4    61.2 1851.67
    77.3 1842.61    96.6 1830.83   119.1 1817.96   138.4  1808.3   148.1 1804.82
   154.6  1803.4   157.8 1802.31   167.5 1797.24   170.7 1796.38   183.6 1796.42
     203 1795.26   209.9 1794.56     216 1794.14   224.9 1795.01   232.1  1797.8
   241.8 1799.29     258 1804.28   270.9 1809.12   283.7 1814.83   290.1 1816.76
   296.4 1819.14   321.9 1831.42     341 1842.11   356.9 1852.16   372.8 1861.37
#Mann= 3 ,-1 , 0
       0     .12       0   209.9    .045       0   224.9     .12       0
Bank Sta=209.9,224.9
XS Rating Curve= 0 ,0
Exp/Cntr=0.3,0.1

Type RM Length L Ch R = 1 ,11314.1 ,501.5,505.2,506.2
XS GIS Cut Line= 4
     1987683.603      187396.164     1987746.103      187229.498
     1987747.839      187113.178     1987794.714      187029.845
#Sta/Elev= 30
       0 1854.35      13  1848.8      55 1828.84    80.9 1817.78    90.6 1814.88
   113.3 1806.56   126.2 1802.94   155.4 1795.94   168.3 1791.07   181.2 1787.78
   184.5 1786.32   187.7 1784.25   190.9 1782.61   194.5 1782.08   203.8  1781.5
   207.1 1781.56   209.5 1781.99   213.6 1783.24   226.5 1784.26   239.4 1786.12
   242.6 1787.32   258.8 1798.38   265.2 1801.91   278.2 1807.95   300.7  1819.6
   319.8 1831.49   345.3 1848.36   351.7 1853.04   364.4 1863.18   389.9 1881.42
#Mann= 3 ,-1 , 0
       0     .12       0   194.5    .045       0   209.5     .12       0
Bank Sta=194.5,209.5
XS Rating Curve= 0 ,0
Exp/Cntr=0.3,0.1

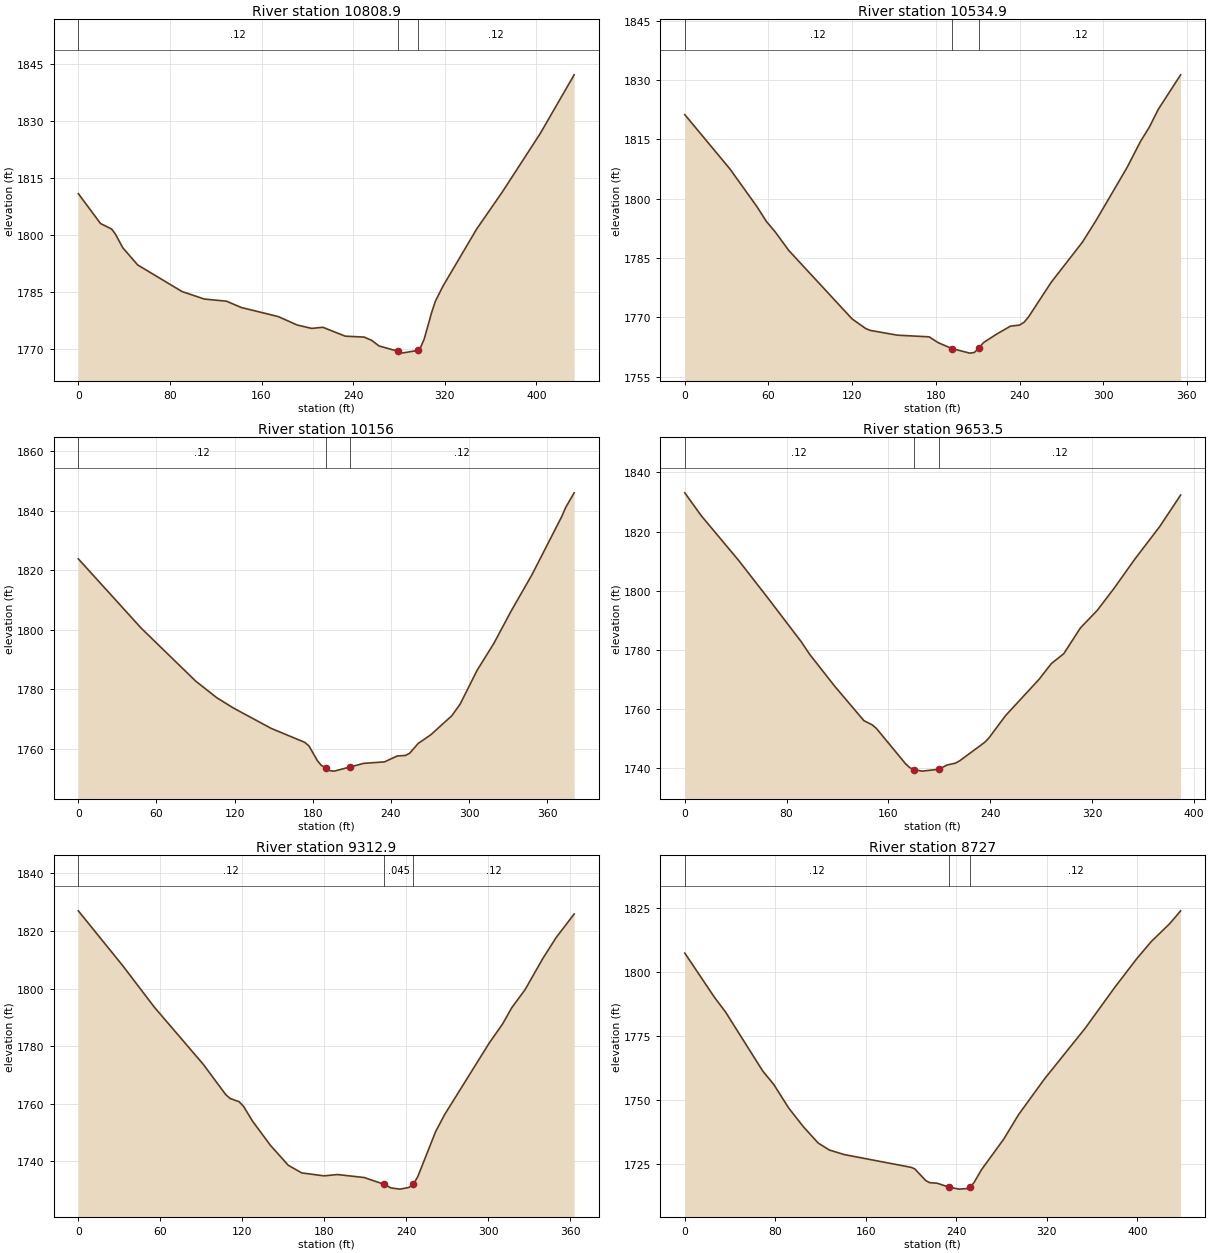
Type RM Length L Ch R = 1 ,10808.9 ,273.4,274,272.4
XS GIS Cut Line= 3
     1988034.298      187469.081     1988199.228      187328.456
     1988220.062      187113.178
#Sta/Elev= 30
       0 1810.94    19.4 1803.06    29.1 1801.61    32.4 1800.27    38.8 1796.69
    51.8 1792.16    90.6 1785.14     110 1783.17   129.4  1782.6   142.3 1780.94
   174.7 1778.54   190.9 1776.35   203.8 1775.43   213.5 1775.73   233.1 1773.39
   249.5 1773.15   256.1  1772.3   262.6 1770.81     279 1769.42   282.3 1768.92
   296.2 1769.62   298.7 1770.31     302  1772.6   308.5 1779.57   311.8 1782.59
   318.3  1786.5   347.8 1801.58   370.8 1811.62   403.5 1826.84     433 1842.24
#Mann= 3 ,-1 , 0
       0     .12       0     279    .045       0   296.2     .12       0
Bank Sta=279,296.2
XS Rating Curve= 0 ,0
Exp/Cntr=0.3,0.1

Type RM Length L Ch R = 1 ,10534.9 ,388.6,378.9,368.2
XS GIS Cut Line= 3
     1988440.548      187522.901     1988457.909      187260.748
     1988445.756      187168.734
#Sta/Elev= 30
       0 1821.24    32.4 1807.49    51.9 1797.88    58.4 1794.27    64.9 1791.55
    74.6 1786.87     120 1769.56   129.7 1767.14     133 1766.67   152.4 1765.46
   175.2 1765.04   181.6 1763.58   191.4 1762.09   204.3 1760.92   207.6 1761.08
   210.8 1762.17   214.1 1763.57   223.8 1765.78   233.5 1767.74     240 1768.01
   243.3 1768.74   246.5  1770.1   262.7 1778.83   285.1 1788.99   294.7 1794.38
   317.1 1807.87   326.7 1814.44   333.1  1818.1   339.5 1822.59   355.5 1831.31
#Mann= 3 ,-1 , 0
       0     .12       0   191.4    .045       0   210.8     .12       0
Bank Sta=191.4,210.8
XS Rating Curve= 0 ,0
Exp/Cntr=0.3,0.1

Type RM Length L Ch R = 1 ,10156   ,491.3,502.5,510.8
XS GIS Cut Line= 4
     1988817.284      187522.901     1988832.909      187356.234
     1988789.506      187248.595     1988789.506      187151.373
#Sta/Elev= 30
       0 1823.82    48.3 1800.55    90.1  1782.8   106.2 1777.25   119.1 1773.75
   148.1 1766.92   173.8 1762.25   177.1 1761.03   183.5 1756.13   186.7 1754.44
     190 1753.76   193.2 1752.72   196.4 1752.58   208.3 1753.93     219 1755.18
   235.1 1755.69   244.8 1757.66   251.2 1757.85   254.4 1758.58   260.9 1761.86
   270.6 1764.77   286.7 1771.14   293.2  1775.1   306.1 1786.35   319.1  1795.5
   332.1 1806.13   348.3 1818.49     371 1837.87   374.2 1841.08   380.7 1845.98
#Mann= 3 ,-1 , 0
       0     .12       0     190    .045       0   208.3     .12       0
Bank Sta=190,208.3
XS Rating Curve= 0 ,0
Exp/Cntr=0.3,0.1

Type RM Length L Ch R = 1 ,9653.5  ,331.8,340.6,348.1
XS GIS Cut Line= 3
     1989259.992      187495.123     1989272.145      187184.359
     1989253.048       187107.97
#Sta/Elev= 30
       0 1833.11    13.1 1825.28    42.6 1810.09    65.5  1797.4    91.7 1782.61
    98.2 1778.42   117.8 1767.67   140.8 1755.99   147.3 1754.58   150.6 1753.37
   173.5 1741.41   176.8 1740.11     180 1739.44   186.6 1738.92   199.7 1739.55
   206.2    1741   212.8 1741.63   216.1 1742.43   235.7 1748.66     239 1750.14
   252.1 1757.71   278.3 1769.92   288.1 1775.32   297.9 1778.69     311 1787.42
   324.1 1793.29   337.2 1800.68   353.6 1810.61   373.3 1821.71   389.7 1832.35
#Mann= 3 ,-1 , 0
       0     .12       0     180    .045       0   199.7     .12       0
Bank Sta=180,199.7
XS Rating Curve= 0 ,0
Exp/Cntr=0.3,0.1

Type RM Length L Ch R = 1 ,9312.9  ,585.9,585.9,582.7
XS GIS Cut Line= 2
     1989509.992      187535.053     1989648.881      187199.984
#Sta/Elev= 30
       0 1827.03    32.7 1807.84    55.6 1793.56    91.5 1773.64   107.8 1763.19
   111.1 1761.81   117.6 1760.72   120.9 1759.06   127.4 1753.98   140.5 1745.56
   153.6 1738.61   163.4 1735.97   179.7 1734.94   189.5  1735.4   209.1 1734.36
   223.7 1732.01   228.7 1730.75   235.3 1730.33   241.8 1730.91   245.1 1732.02
   248.3 1734.66   261.4 1750.35     268 1756.27   300.6 1781.11   310.4 1787.76
     317 1793.32   326.8 1799.65   339.8 1810.49   349.6 1817.79   362.7 1825.93
#Mann= 3 ,-1 , 0
       0     .12       0   223.7    .045       0   245.1     .12       0
Bank Sta=223.7,245.1
XS Rating Curve= 0 ,0
Exp/Cntr=0.3,0.1

Type RM Length L Ch R = 1 ,8727    ,223.9,222.5,220.7
XS GIS Cut Line= 3
     1990022.145       187732.97     1990126.312      187422.206
     1990110.687      187312.831
#Sta/Elev= 30
       0 1807.46    26.2 1790.14      36 1784.38    68.8 1761.31    78.7 1755.93
    91.8 1746.76   104.9 1739.36     118 1732.98   127.8 1730.28   140.9  1728.5
   199.9 1723.51   203.2 1722.91     213  1718.3   216.3  1717.5   222.9 1717.29
   233.9 1715.68   242.5 1714.96   248.9 1715.16   252.4 1715.92   255.6 1717.52
   262.2 1722.57   281.9 1734.57     295 1744.17   317.9 1758.15   353.8 1777.97
   379.8 1793.91   399.2 1805.13   412.2 1811.96   428.5 1818.97   438.2 1824.02
#Mann= 3 ,-1 , 0
       0     .12       0   233.9    .045       0   252.4     .12       0
Bank Sta=233.9,252.4
XS Rating Curve= 0 ,0
Exp/Cntr=0.3,0.1

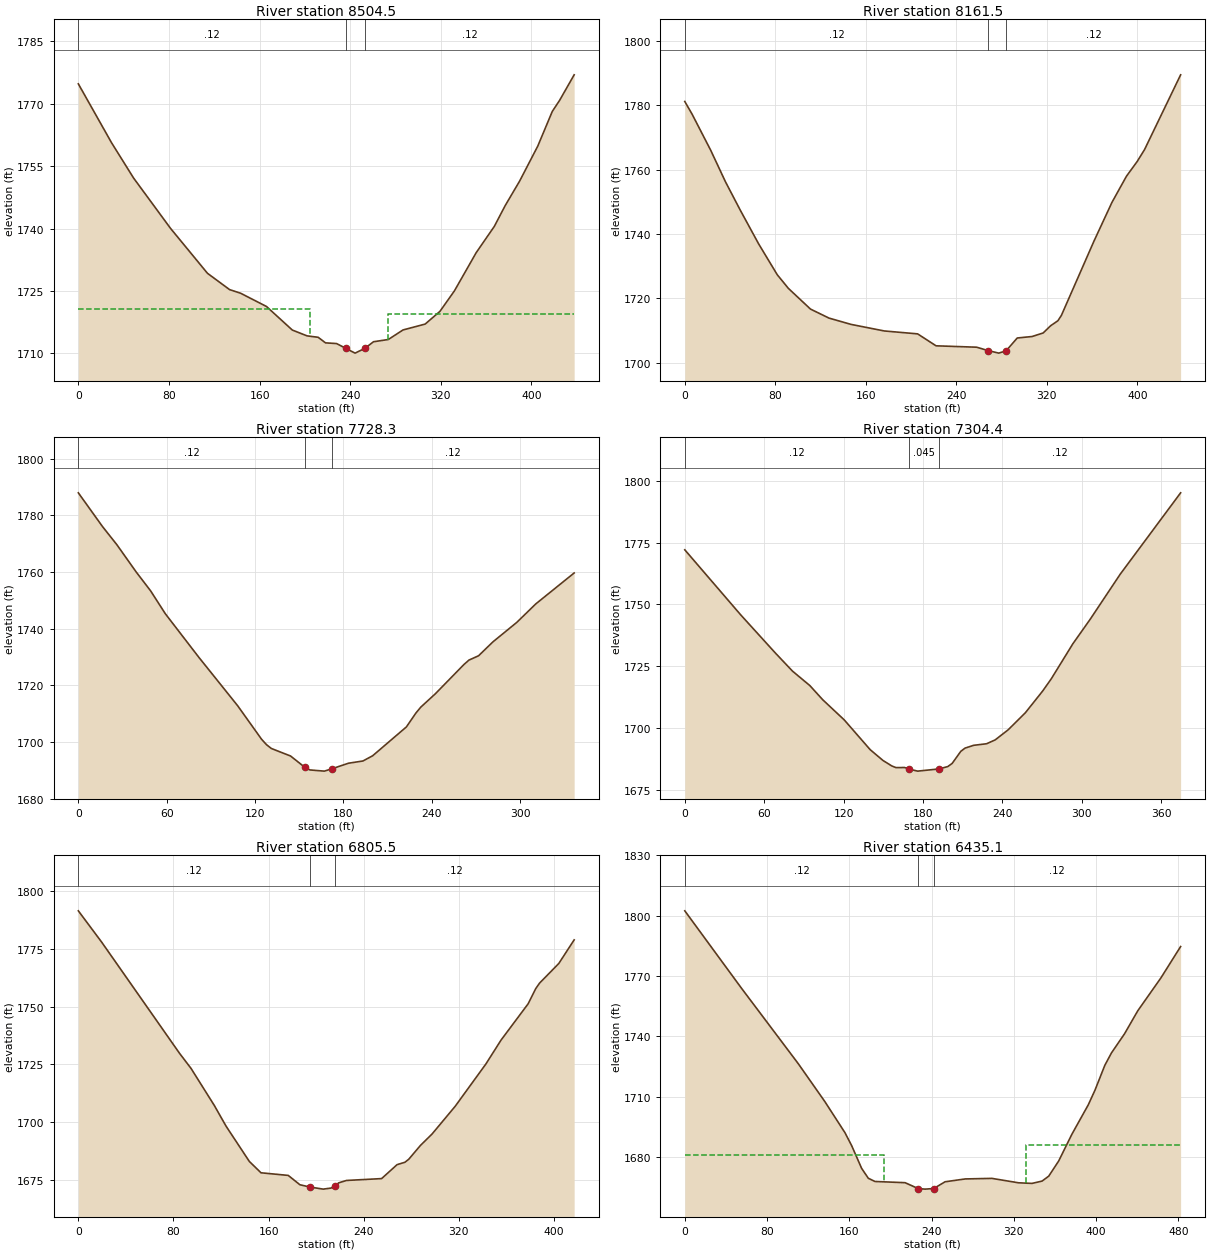
Type RM Length L Ch R = 1 ,8504.5  ,315.5,343,369.3
XS GIS Cut Line= 3
     1990254.784      187786.789     1990334.645      187477.762
     1990312.076      187361.442
#Sta/Elev= 30
       0 1774.81    29.3 1760.66    48.8 1752.15    81.4 1740.05     114 1729.25
   133.5 1725.33   143.3 1724.45   166.1 1721.27   188.9  1715.6   201.9  1714.2
   211.7 1713.86   218.2 1712.52     228 1712.35   236.1  1711.2   244.3 1710.05
  252.95  1711.2   260.6 1712.79   273.6 1713.32   286.6 1715.62   306.2 1717.04
   319.2 1720.09     332 1725.02   351.2  1734.2   367.2 1740.52   376.8 1745.52
   389.6 1751.44   405.6 1759.85   418.4 1768.18   424.9 1770.86   437.7 1776.98
#Mann= 3 ,-1 , 0
       0     .12       0   236.1    .045       0  252.95     .12       0
#XS Ineff= 2 , 0
          204.55 1720.61  273.44         1719.45
Permanent Ineff=
       F       F
Bank Sta=236.1,252.95
XS Rating Curve= 0 ,0
Exp/Cntr=0.3,0.1

Type RM Length L Ch R = 1 ,8161.5  ,437.3,433.2,427.5
XS GIS Cut Line= 4
     1990358.951      187833.664     1990487.423      187703.456
     1990629.784      187684.359     1990723.534      187623.595
#Sta/Elev= 30
       0 1781.14     6.5 1777.17    22.9    1766    35.9 1756.24      49 1747.42
    65.3 1736.91    81.7 1727.36    91.5 1723.13   111.1 1716.68   127.4 1713.89
     147 1711.92   176.4 1709.88   205.8 1708.98   222.1 1705.27     258 1704.84
   268.1 1703.79   277.6    1703   284.1 1703.75   293.9  1707.7     307 1708.16
   316.8 1709.26   323.3 1711.48   329.8 1713.05   332.9 1714.71   361.7 1737.78
   377.6 1749.81   390.4 1757.92     400 1762.56   406.4  1766.2   438.3 1789.42
#Mann= 3 ,-1 , 0
       0     .12       0   268.1    .045       0   284.1     .12       0
Bank Sta=268.1,284.1
XS Rating Curve= 0 ,0
Exp/Cntr=0.3,0.1

Type RM Length L Ch R = 1 ,7728.3  ,431.9,423.9,413.9
XS GIS Cut Line= 3
     1990513.464      188165.262     1990749.576       188076.72
     1990832.909      188062.831
#Sta/Elev= 30
       0 1787.98    16.4 1776.08    26.2 1769.64    39.3 1760.02    49.1 1753.36
      59 1745.34    81.9 1729.86   108.1 1712.87   124.4 1700.99   127.7  1699.1
     131 1697.74   144.1 1695.07   153.9 1691.03   157.2 1690.16     167 1689.74
   171.9 1690.52   183.4 1692.53   193.2 1693.32   199.8 1695.16   222.7 1705.34
   229.2 1710.27   232.5 1712.34   242.3 1717.01   261.9 1727.44   265.2 1728.94
   271.7 1730.46   281.4 1735.34   297.7 1742.27   310.6 1748.79   336.6 1759.69
#Mann= 3 ,-1 , 0
       0     .12       0   153.9    .045       0   171.9     .12       0
Bank Sta=153.9,171.9
XS Rating Curve= 0 ,0
Exp/Cntr=0.3,0.1

Type RM Length L Ch R = 1 ,7304.4  ,495,498.9,499.3
XS GIS Cut Line= 2
     1990747.839      188581.928     1991020.409      188324.984
#Sta/Elev= 30
       0 1772.08    42.3 1745.76    68.4  1730.4    81.4 1723.05    94.5 1717.21
   104.2  1711.5   120.5 1703.33   140.1  1691.3   149.8 1686.93   156.4 1684.74
   159.6 1684.07   166.1 1684.11   169.4 1683.48   175.9 1682.65   192.1 1683.54
   198.7 1684.49     202 1685.77   208.5 1690.64   211.7 1691.94   218.2 1693.08
     228 1693.71   234.5 1695.27   244.3 1699.34   257.3 1706.24   270.4 1715.04
   276.9 1719.97   293.2 1734.12   306.2 1743.95     329 1762.26   374.6 1795.11
#Mann= 3 ,-1 , 0
       0     .12       0   169.4    .045       0   192.1     .12       0
Bank Sta=169.4,192.1
XS Rating Curve= 0 ,0
Exp/Cntr=0.3,0.1

Type RM Length L Ch R = 1 ,6805.5  ,378.2,370.3,360.7
XS GIS Cut Line= 3
     1991008.256      188967.345     1991239.159      188785.053
     1991291.242      188673.942
#Sta/Elev= 30
       0 1791.37    19.6 1777.86      85 1729.86    94.8 1723.24   114.4  1707.2
   124.2 1698.32   143.8 1683.05   153.6 1678.15   176.5 1677.02   186.3 1672.99
   194.6    1672   205.9 1671.09   212.5 1671.55   215.7 1672.56     219 1673.82
   225.5 1674.84     255 1675.64     268 1681.67   274.6  1682.7   277.8 1683.99
   287.6 1689.94   297.4  1694.9   316.8 1706.85   342.6 1725.11   355.5 1735.56
   378.2 1751.18   384.6 1757.75   387.8 1760.12     404 1768.62   416.9 1778.82
#Mann= 3 ,-1 , 0
       0     .12       0   194.6    .045       0   215.7     .12       0
Bank Sta=194.6,215.7
XS Rating Curve= 0 ,0
Exp/Cntr=0.3,0.1

Type RM Length L Ch R = 1 ,6435.1  ,515.8,505.4,493.4
XS GIS Cut Line= 4
     1991492.631      189227.762     1991470.062      189050.678
     1991560.339      188892.692     1991551.659      188771.164
#Sta/Elev= 30
       0 1802.41    55.2 1763.92   110.4 1726.46   136.3  1707.6   155.8 1692.19
   162.3 1685.78     172 1674.49   178.5 1669.56     185 1667.96   214.3 1667.36
   227.1 1664.42   233.8 1664.16   242.1 1664.46   253.2 1667.81   272.8 1669.22
   298.7  1669.5   324.7  1667.3   337.7    1667   347.5 1668.15     354  1670.6
   363.7 1678.15   376.5 1691.39   392.5 1706.06     399 1713.32   408.6  1725.7
     415  1731.8   427.8 1741.37   440.6 1752.74   463.1 1769.07   482.3 1784.67
#Mann= 3 ,-1 , 0
       0     .12       0   227.1    .045       0   242.1     .12       0
#XS Ineff= 2 , 0
          193.89  1681.2  331.68         1686.29
Permanent Ineff=
       F       F
Bank Sta=227.1,242.1
XS Rating Curve= 0 ,0
Exp/Cntr=0.3,0.1

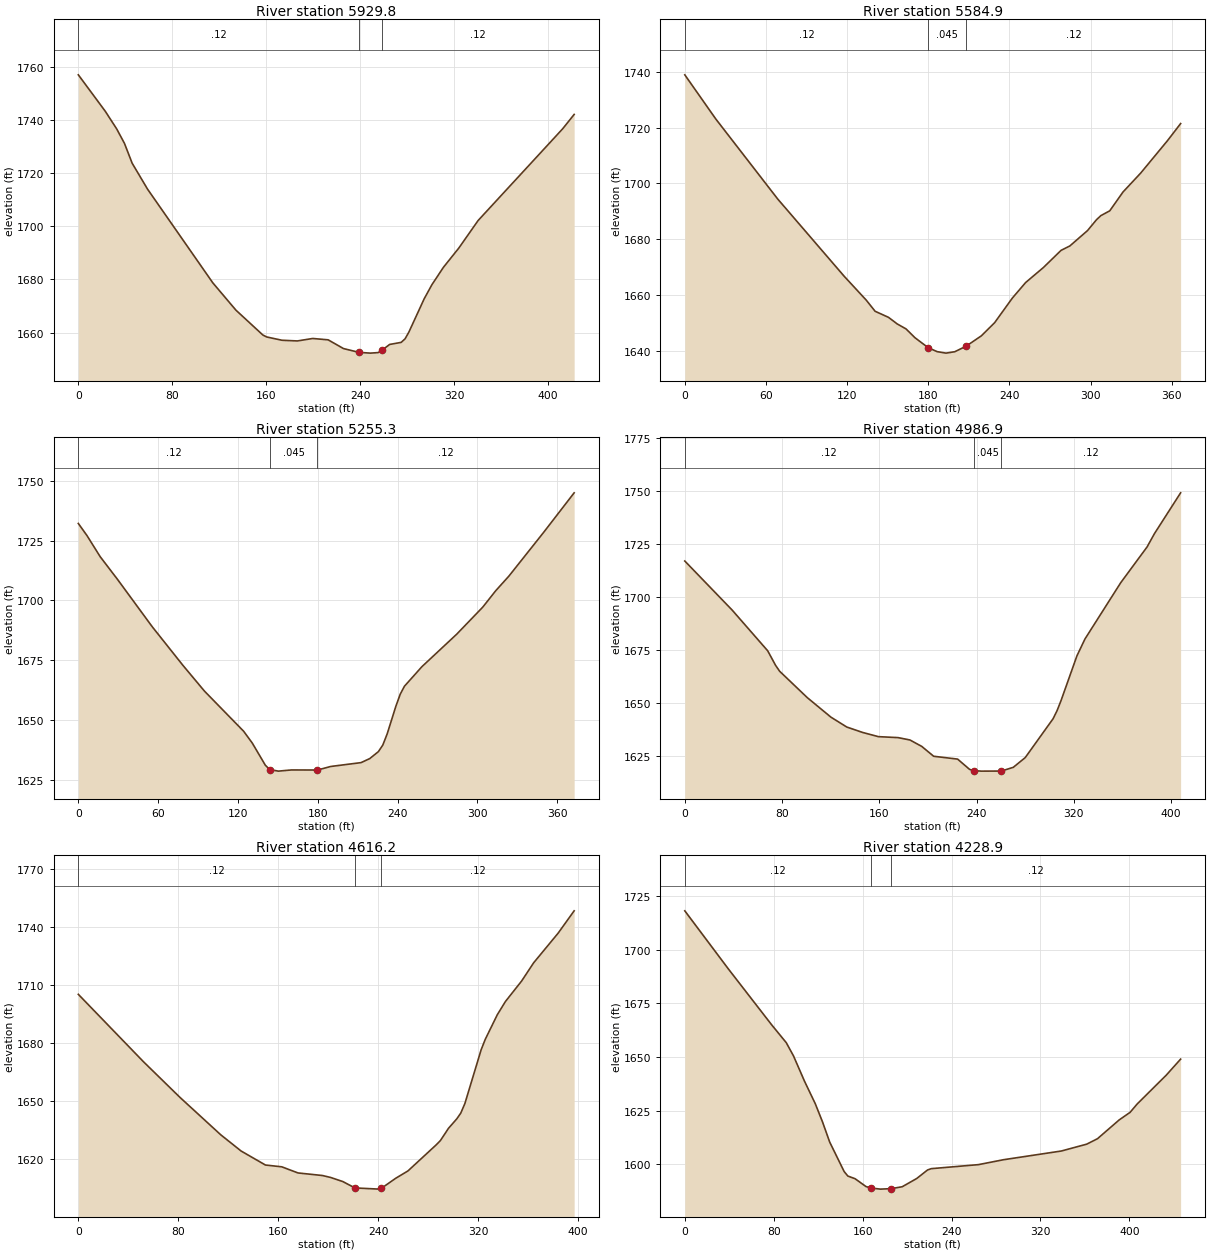
Type RM Length L Ch R = 1 ,5929.8  ,342.3,344.9,347.2
XS GIS Cut Line= 2
     1991956.173      189146.164     1991971.798      188724.289
#Sta/Elev= 30
       0  1757.1    22.9  1743.4    32.7  1736.7    39.3 1731.26    45.8 1723.83
    58.9 1714.06   114.5 1678.74   134.2 1668.44   157.1 1659.09   160.4 1658.34
   173.4  1657.1   186.5 1656.84   199.6 1657.77   212.7 1657.26   225.8 1653.97
   238.8 1652.55   248.7 1652.25   255.3 1652.45   258.5 1653.33   265.1 1655.52
   274.9  1656.3   278.2 1657.63   281.4 1660.11   294.5 1672.72   301.1 1678.04
   310.9 1684.59     324 1691.84   340.4  1702.2   412.4 1736.76   422.2 1742.17
#Mann= 3 ,-1 , 0
       0     .12       0   238.8    .045       0   258.5     .12       0
Bank Sta=238.8,258.5
XS Rating Curve= 0 ,0
Exp/Cntr=0.3,0.1

Type RM Length L Ch R = 1 ,5584.9  ,319.6,329.6,337.4
XS GIS Cut Line= 2
     1992272.145      189160.053     1992324.228      188797.206
#Sta/Elev= 30
       0 1738.95    22.9 1723.12    68.7  1694.4   117.8 1666.71   134.2  1658.1
   140.7 1654.13   150.6 1651.95   157.1 1649.57   163.6 1647.79   170.2 1644.63
     180 1641.05   186.6 1639.64   193.1 1639.11   199.6 1639.61   208.1 1641.62
   219.3 1645.33   229.1 1650.04   242.2 1658.87     252 1664.43   265.1  1669.8
   278.2 1675.98   284.7 1677.56   297.8 1683.09   304.4 1686.97   307.6 1688.43
   314.2 1690.16     324 1696.91   337.1 1703.72   356.8 1715.28   366.6 1721.46
#Mann= 3 ,-1 , 0
       0     .12       0     180    .045       0   208.1     .12       0
Bank Sta=180,208.1
XS Rating Curve= 0 ,0
Exp/Cntr=0.3,0.1

Type RM Length L Ch R = 1 ,5255.3  ,281.2,268.4,255.6
XS GIS Cut Line= 2
     1992496.103      189248.595     1992685.339      188927.414
#Sta/Elev= 30
       0 1732.14     6.5 1727.08    16.4 1718.27    29.4  1708.8    55.6 1688.93
    78.5 1672.91    94.8 1662.06   124.3 1645.25   130.8 1640.31   140.6 1631.06
   143.9 1629.22   150.4 1628.58   160.2 1629.07   179.8 1629.04   189.7 1630.52
   212.6 1632.14   219.1 1633.82   225.6 1636.73   228.9 1639.45   232.2 1644.12
   238.7 1655.63     242 1660.71   245.2 1664.08   258.3 1672.24   284.5 1685.84
   304.1 1697.17   313.9 1704.06   323.7  1710.1   349.9 1728.45   372.8 1744.95
#Mann= 3 ,-1 , 0
       0     .12       0   143.9    .045       0   179.8     .12       0
Bank Sta=143.9,179.8
XS Rating Curve= 0 ,0
Exp/Cntr=0.3,0.1

Type RM Length L Ch R = 1 ,4986.9  ,374.8,370.7,362.1
XS GIS Cut Line= 4
     1992905.826      189335.401     1992841.589      189151.373
      1992850.27      188984.706     1992841.589      188939.567
#Sta/Elev= 30
       0 1716.94      39 1693.76    68.2 1674.57    74.7 1667.69      78 1664.94
   100.7 1652.51   120.2 1643.27   133.2 1638.62   146.2 1636.07   159.2 1634.08
   175.4 1633.62   185.2  1632.5   194.9 1629.47   204.7 1624.82   224.4 1623.48
   234.2 1618.64   237.5 1618.03     244 1617.81   260.4 1617.84   270.2 1619.61
     280  1624.2   302.9 1642.52   306.2 1646.36   309.4 1651.02   322.5 1672.17
   329.1 1680.13   358.5 1706.68   380.2 1723.57   386.3 1729.89   407.8 1749.11
#Mann= 3 ,-1 , 0
       0     .12       0   237.5    .045       0   260.4     .12       0
Bank Sta=237.5,260.4
XS Rating Curve= 0 ,0
Exp/Cntr=0.3,0.1

Type RM Length L Ch R = 1 ,4616.2  ,381.3,387.3,391.8
XS GIS Cut Line= 3
     1993237.423      189217.345     1993145.409      188904.845
     1993096.798      188852.762
#Sta/Elev= 30
       0 1705.17    52.1 1670.43    81.4 1651.98     114 1632.72   130.3 1624.34
   149.8  1617.1   162.9 1616.17   175.9 1613.01   195.5 1611.68     202 1610.68
   211.8 1608.56   221.5 1605.27   241.1 1604.66  242.53 1605.02   254.1 1610.25
   263.9 1614.04   286.7  1627.6   289.9 1629.71   296.4 1636.05     303 1640.91
   306.2 1643.87   309.5 1648.81   322.5 1676.52   325.8 1681.92   335.5 1694.69
     342 1701.49   354.9 1712.01   364.6 1721.47   384.1 1736.68     397 1748.26
#Mann= 3 ,-1 , 0
       0     .12       0   221.5    .045       0  242.53     .12       0
Bank Sta=221.5,242.53
XS Rating Curve= 0 ,0
Exp/Cntr=0.3,0.1

Type RM Length L Ch R = 1 ,4228.9  ,477,504.5,529.8
XS GIS Cut Line= 3
     1993560.339       189107.97     1993518.673      188840.609
     1993442.284      188682.623
#Sta/Elev= 30
       0 1718.16    39.1 1691.14    78.2 1664.99    91.3 1656.69    97.8 1650.53
   107.6 1638.86   117.4 1628.24   123.9 1619.78   130.4 1610.33   143.4  1596.6
   146.7 1594.53   153.2 1593.28     163 1589.64   167.5 1588.95     176 1588.43
   185.8 1588.66   195.6 1589.54   208.6 1593.36   218.4 1597.35   221.7 1597.97
   264.1 1599.84   286.8 1602.14   338.8  1606.2   361.6 1609.39   371.3 1611.93
   390.8 1620.68   400.6 1624.21   407.1 1628.16   433.1 1641.52   446.1 1649.03
#Mann= 3 ,-1 , 0
       0     .12       0   167.5    .045       0   185.8     .12       0
Bank Sta=167.5,185.8
XS Rating Curve= 0 ,0
Exp/Cntr=0.3,0.1

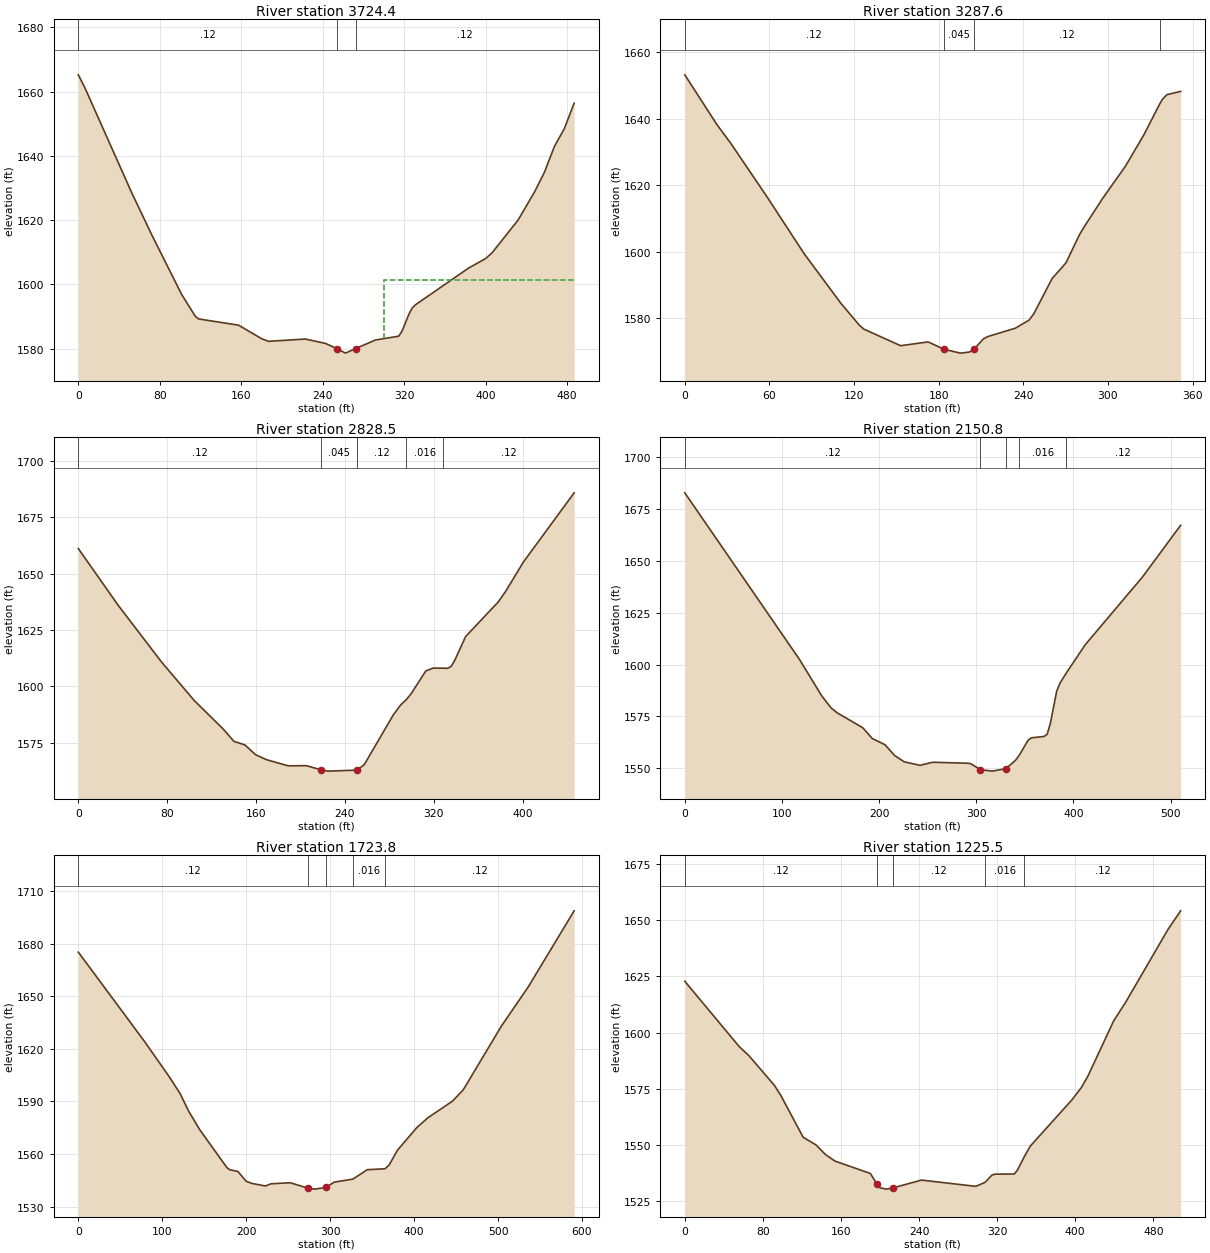
Type RM Length L Ch R = 1 ,3724.4  ,430.4,436.7,442.1
XS GIS Cut Line= 3
     1993779.089       189139.22     1994093.326      188943.039
     1994207.909      188922.206
#Sta/Elev= 30
       0  1665.2     6.6 1661.06    52.4 1628.54    72.1 1615.43   101.6 1596.82
   114.7 1590.18     118 1589.28   157.4 1587.33   180.3 1583.07   186.9 1582.31
   222.9 1583.02   242.6 1581.67     254 1580.03   262.3 1578.64   272.3 1580.06
   291.8 1582.73   314.7 1583.91     318 1585.56   324.6 1590.73   327.8 1592.65
   331.1 1593.69   383.4 1605.13   399.6 1607.98     406 1609.73   431.9 1620.05
   448.1 1628.84   457.8 1634.96   467.5 1642.92   477.2 1648.41   486.9  1656.4
#Mann= 3 ,-1 , 0
       0     .12       0     254    .045       0   272.3     .12       0
#XS Ineff= 2 , 0
                          300.43         1601.43
Permanent Ineff=
       F       F
Bank Sta=254,272.3
XS Rating Curve= 0 ,0
Exp/Cntr=0.3,0.1

Type RM Length L Ch R = 1 ,3287.6  ,459.6,459.1,458.3
XS GIS Cut Line= 2
     1993937.076      189463.873     1994273.881      189363.178
#Sta/Elev= 30
       0  1653.2    22.8 1638.23    32.6 1632.61    58.6 1616.34    84.6 1599.46
   110.7 1584.52   123.7 1577.98   126.9 1576.79     153  1571.8   172.5 1572.94
   183.6 1570.76   195.3 1569.57   201.8 1569.89   205.1 1570.79   211.6 1573.83
   214.8 1574.55   234.4 1577.07   244.1  1579.5   247.4 1581.37   260.4 1591.98
   270.2 1596.68   279.9 1605.25   283.2 1607.56   296.2 1616.05   312.5 1625.82
   325.5  1635.2  336.641644.412   338.5 1645.79   341.8 1647.24   351.5 1648.22
#Mann= 4 ,-1 , 0
       0     .12       0   183.6    .045       0   205.1     .12       0
  336.64    .016       0
Bank Sta=183.6,205.1
XS Rating Curve= 0 ,0
Exp/Cntr=0.3,0.1

Type RM Length L Ch R = 1 ,2828.5  ,686.2,677.7,666.6
XS GIS Cut Line= 2
      1994006.52      189927.414     1994430.131      189786.789
#Sta/Elev= 30
       0 1661.04    35.8 1635.98    74.9  1610.8   104.3 1593.76   130.3 1581.16
   140.1 1575.63   149.9 1574.09   159.6 1569.73   169.4 1567.52     189  1564.8
   205.2 1564.88   218.3 1563.06   224.8 1562.46   250.9  1562.9   257.4 1565.35
   283.4 1587.29     290  1591.7   295.11594.084   299.7 1596.83   312.8 1606.87
   319.3  1608.1   328.51608.078   332.3 1607.99   335.6 1608.85   338.8 1611.52
   348.6 1622.07   377.9 1637.37   384.4 1641.91   400.7 1655.15   446.3 1685.75
#Mann= 5 ,-1 , 0
       0     .12       0   218.3    .045       0   250.9     .12       0
   295.1    .016       0   328.5     .12       0
Bank Sta=218.3,250.9
XS Rating Curve= 0 ,0
Exp/Cntr=0.3,0.1

Type RM Length L Ch R = 1 ,2150.8  ,421.1,427,431
XS GIS Cut Line= 2
     1994358.951      190463.873     1994740.895      190125.331
#Sta/Elev= 30
       0 1682.66   117.8 1602.61   140.7  1585.1   150.5 1579.14     157  1576.7
   183.2 1569.54     193 1564.37   206.1 1561.37   215.9 1556.22   225.8 1553.17
   242.1 1551.45   255.2 1552.93   291.2 1552.47   294.4 1552.24   304.3 1549.36
   316.6 1548.66   330.4 1549.82   340.3  1553.8   344.31556.311   353.3 1563.47
   356.6 1564.68   369.7 1565.34     373  1566.4   376.2  1571.4   382.8 1587.11
   386.1 1590.89  392.161595.508   412.2 1609.52   471.1 1642.11   510.4 1667.01
#Mann= 5 ,-1 , 0
       0     .12       0   304.3    .045       0   330.4     .12       0
   344.3    .016       0  392.16     .12       0
Bank Sta=304.3,330.4
XS Rating Curve= 0 ,0
Exp/Cntr=0.3,0.1

Type RM Length L Ch R = 1 ,1723.8  ,499.7,498.3,495.5
XS GIS Cut Line= 3
     1994523.881      190753.803     1994917.978       190545.47
     1995022.145      190444.776
#Sta/Elev= 30
       0 1675.18    78.7 1624.29   108.2 1604.12   121.3 1594.41   131.1 1584.69
   144.2 1574.14     177 1552.19   180.3    1551   190.1 1549.98   199.9 1544.43
   206.5 1543.21   222.9  1541.7   229.4 1542.95   252.4 1543.57   273.4 1540.48
   281.9 1539.92     295 1540.93   304.8 1543.92     3271545.633   344.2 1551.02
  365.29 1551.54   370.4 1553.82   380.2 1562.18   403.2 1575.04   416.3 1580.62
   445.8 1590.18   458.6 1596.68   503.7 1632.79   535.9 1655.33   590.6 1698.76
#Mann= 5 ,-1 , 0
       0     .12       0   273.4    .045       0     295     .12       0
     327    .016       0  365.29     .12       0
Bank Sta=273.4,295
XS Rating Curve= 0 ,0
Exp/Cntr=0.3,0.1

Type RM Length L Ch R = 1 ,1225.5  ,706.6,704.1,700.5
XS GIS Cut Line= 2
     1994766.937      191191.303     1995188.812      190908.317
#Sta/Elev= 30
       0 1622.88    55.7 1593.76    65.6 1589.75    91.8 1576.47    98.3 1572.03
   121.3  1553.3   134.4 1549.92   144.2 1545.59     154 1542.66   190.1 1537.18
   196.6 1532.63   199.9 1530.81   206.5 1530.19     213 1530.71   242.5 1534.22
   298.2 1531.43  307.531533.182   314.6 1536.42   317.9 1536.87   337.6 1536.93
   340.8 1538.68  348.041544.821     354 1549.38   396.6 1569.98   406.4 1575.54
     413 1580.57   439.2 1605.04   452.3 1613.96   494.9 1645.87     508 1654.28
#Mann= 5 ,-1 , 0
       0     .12       0   196.6    .045       0     213     .12       0
  307.53    .016       0  348.04     .12       0
Bank Sta=196.6,213
XS Rating Curve= 0 ,0
Exp/Cntr=0.3,0.1

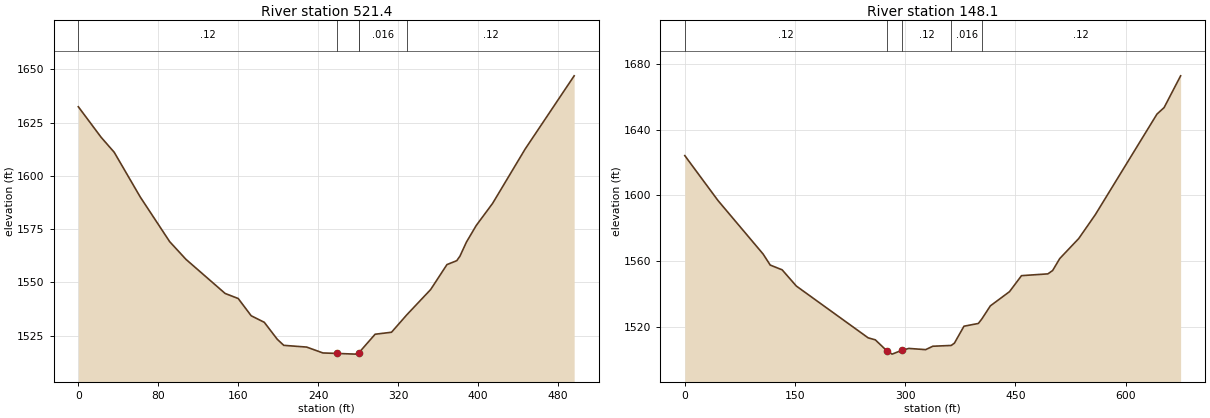
Type RM Length L Ch R = 1 ,521.4   ,372.3,373.2,373.5
XS GIS Cut Line= 2
     1995214.853      191672.206     1995575.964      191331.928
#Sta/Elev= 30
       0 1632.41    22.8 1618.09    35.9 1611.06      62 1590.05    91.4 1569.13
   107.7 1560.82   146.9 1544.82     160 1542.44     173 1534.35   186.1 1531.28
   199.1 1523.31   205.6 1520.47   228.5 1519.66   244.8  1516.9   258.7 1516.68
   277.5 1516.35   280.7 1516.95  280.771516.989     297 1525.68   313.4 1526.61
  328.781534.826   352.6 1546.66   368.9 1558.36   378.7 1560.19   381.9 1562.31
   388.4 1568.92   398.2  1576.7   414.6 1587.09   447.2  1612.6   496.2 1646.92
#Mann= 5 ,-1 , 0
       0     .12       0   258.7    .045       0   280.7     .12       0
  280.77    .016       0  328.78     .12       0
Bank Sta=258.7,280.7
XS Rating Curve= 0 ,0
Exp/Cntr=0.3,0.1

Type RM Length L Ch R = 1 ,148.1   ,139.8,148.1,155.4
XS GIS Cut Line= 4
     1995397.145      191884.012     1995560.339      191844.081
     1995813.812      191623.595     1995843.326      191455.192
#Sta/Elev= 30
       0 1624.14    45.2 1596.81   106.6 1564.28   116.3 1557.57   132.5 1554.68
   151.8 1544.82   249.6 1513.31   259.3  1512.1     275 1505.44   282.2 1503.41
   295.2  1505.7     305 1506.88   327.8 1506.14   337.6 1508.21  362.651508.682
     367  1510.1     380 1520.38   399.6 1522.07  404.351524.822   415.9 1532.75
     442 1541.41   458.3 1551.13   494.2 1552.22   500.7 1554.26   510.4 1561.55
   536.2 1573.71   558.8 1588.23   642.7 1649.39   652.4 1653.34   674.9 1672.66
#Mann= 5 ,-1 , 0
       0     .12       0     275    .045       0   295.2     .12       0
  362.65    .016       0  404.35     .12       0
Bank Sta=275,295.2
XS Rating Curve= 0 ,0
Exp/Cntr=0.3,0.1

Chan Stop Cuts=-1
Use User Specified Reach Order=0
Composite Channel Slope=5